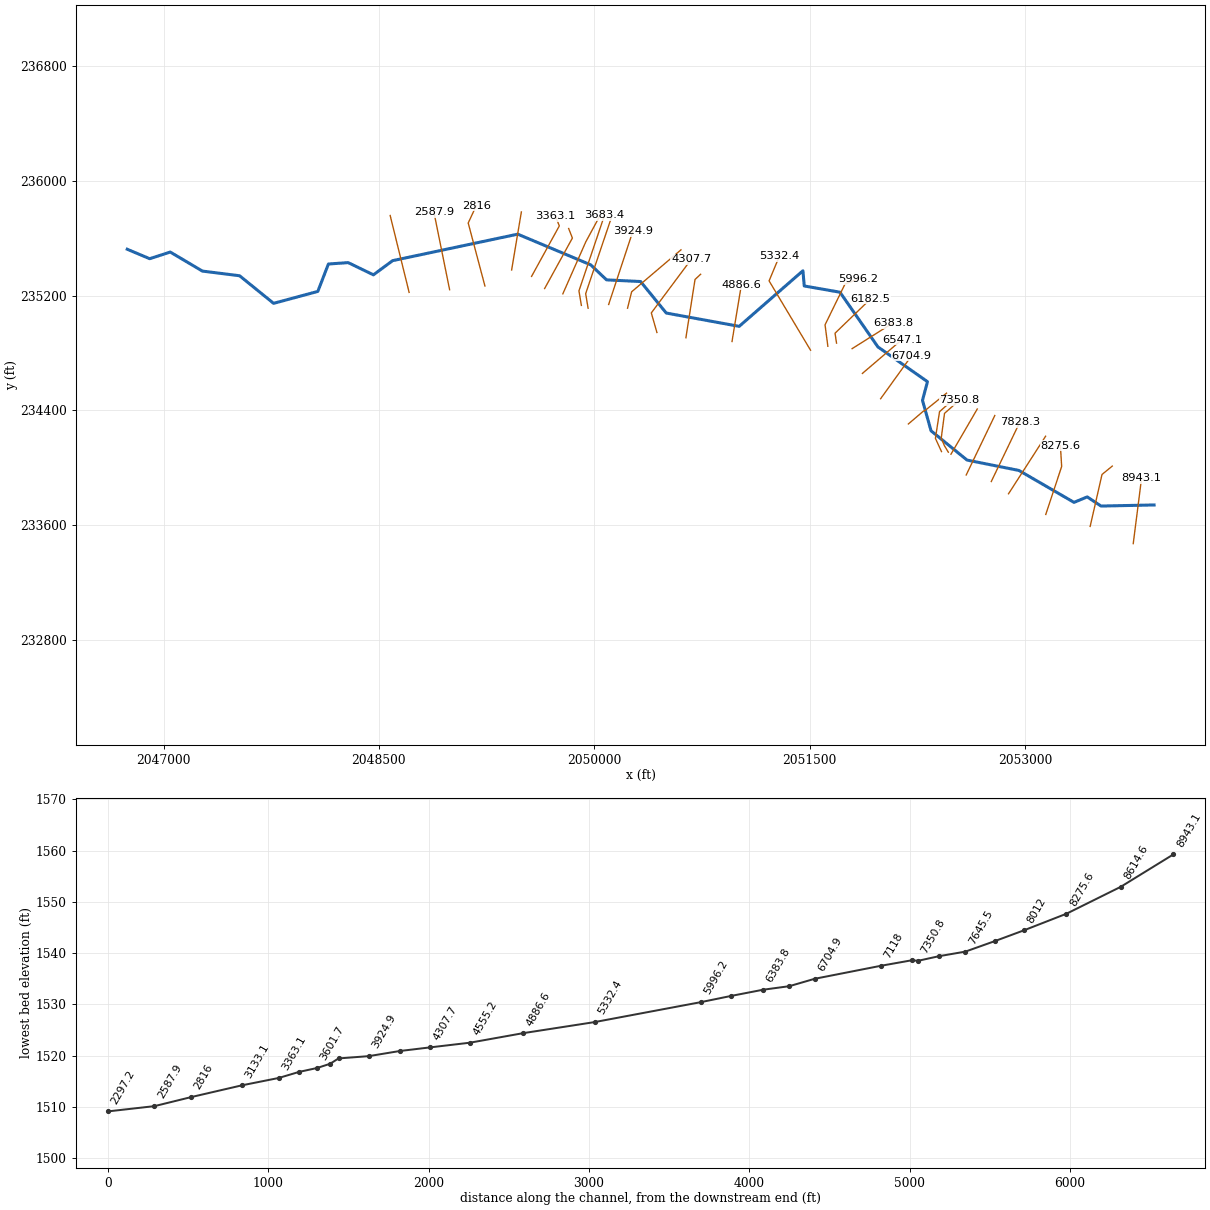
--- WINDCK.prj (project) ---

Proj Title=WINDCK
Current Plan=p01
Default Exp/Contr=0,0
English Units
Geom File=g01
Flow File=f01
Plan File=p01
BEGIN DESCRIPTION:
END DESCRIPTION:
DSS Export Rating Curves= 0
DSS Export Rating Curve Sorted= 0
DSS Export Volume Flow Curves= 0
DXF Filename=.\backup\WINDCK.
DXF OffsetX= 0
DXF OffsetY= 0
DXF ScaleX= 0
DXF ScaleY= 0

--- WINDCK.p01 (plan) ---

Plan Title=Floodplain
Program Version=4.00
Geom File=g01
Flow File=f01
K Sum by GR=0
Std Step Tol=0.01
Critical Tol=0.01
Num of Std Step Trials=20
Max Error Tol=0.3
Flow Tol Ratio=0.001
Split Flow NTrial=30
Split Flow Tol=0.02
Split Flow Ratio=0.02
Log Output Level=0
Friction Slope Method=1
Unsteady Friction Slope Method=2
Unsteady Bridges Friction Slope Method=1
Global Log Level=0
CheckData=False
Run HTab=0
Run UNet=0
Run PostProcess=0
UNET Theta=0
UNET Theta Warmup=0
UNET ZTol=0
UNET ZSATol=0
UNET MxIter=0
UNET MaxInSteps=0
UNET DtIC=0
UNET DtMin=0
UNET MaxCRTS=0
UNET WFStab=0
UNET SFStab=0
UNET WFX=0
UNET SFX=0
UNET DSS MLevel=0
UNET DZMax Abort=0
UNET Convert EG Bridges=0
UNET Use Existing IB Tables=0
UNET Froude Limit=0
UNET Froude Power=0
Write IC File=0
Echo Input=False
Echo Output=False
Write Detailed=0

--- WINDCK.f01 (steady flow) ---

Flow Title=NFF Regression Equation
Program Version=4.00
Number of Profiles=1
Profile Names=P100yr
River Rch & RM=WINDCK,Main      ,8943.1
544.2585
River Rch & RM=WINDCK,Main      ,8943.1
511.6331
River Rch & RM=WINDCK,Main      ,8012
581.3067
River Rch & RM=WINDCK,Main      ,6182.5
633.9017
River Rch & RM=WINDCK,Main      ,5332.4
682.7974
River Rch & RM=WINDCK,Main      ,3133.1
753.0002
River Rch & RM=WINDCK,Main      ,498.3
800.3183
Boundary for River Rch & Prof#=WINDCK,Main      ,1
Up Type=0
Dn Type=3
Dn Slope=0.01386

--- WINDCK.g01 (geometry) ---

Geom Title=USGS 10m DEM
Program Version=4.10

River Reach=WINDCK          ,Main
Reach XY= 30
     2053899.444       233740.05     2053529.999      233732.411
     2053433.471        233796.3     2053341.805      233758.106
     2052957.777      233981.023     2052596.666      234053.245
     2052345.972      234257.411     2052286.249      234469.911
     2052320.971      234600.467     2051975.835      234842.977
      2051711.58      235224.651     2051462.598      235268.226
     2051453.484      235374.433      2051009.56      234986.585
      2050501.45      235079.308     2050322.597      235299.246
       2050085.7      235310.734     2049975.185      235415.752
     2049466.852      235629.815     2048595.498      235444.919
     2048461.643       235345.96     2048285.578      235431.312
     2048148.102      235421.481     2048074.407      235230.223
     2047766.331      235147.002     2047529.525       235339.54
     2047270.411      235372.092     2047046.452      235504.905
     2046903.223      235458.464     2046746.973      235524.436

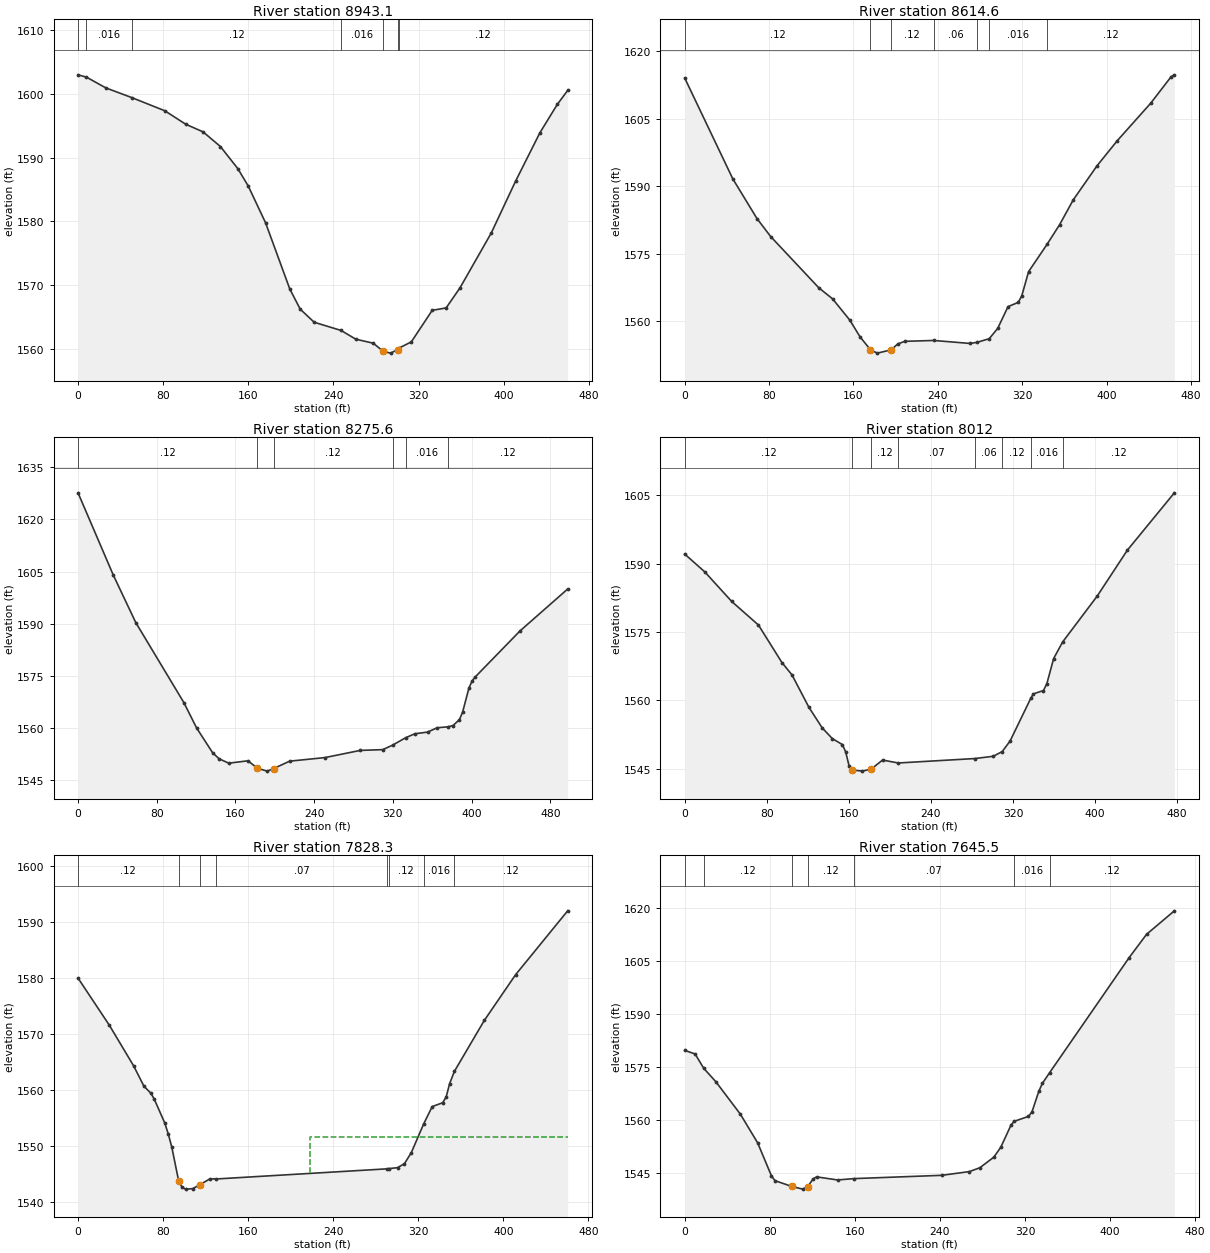
Type RM Length L Ch R = 1 ,8943.1  ,327.1,328.5,324.5
XS GIS Cut Line= 2
     2053754.295      233470.243     2053812.324      233926.652
#Sta/Elev= 30
       0 1602.99    7.961602.623    26.1 1600.94   50.991599.382    81.6 1597.34
   101.2 1595.23   117.5 1594.03   133.8 1591.73   150.1 1588.27   159.9 1585.54
   176.2 1579.76     199 1569.35   208.8 1566.18   221.9 1564.13  247.191562.839
     261 1561.47   277.4 1560.84   286.8 1559.56   293.7 1559.28   300.2 1559.82
  301.35 1560.05   313.2 1561.05   332.8    1566   345.9 1566.38   358.9 1569.53
   388.3 1578.15   411.1 1586.27     434 1593.89   450.3 1598.33   460.1 1600.54
#Mann= 7 ,-1 , 0
       0     .12       0    7.96    .016       0   50.99     .12       0
  247.19    .016       0   286.8    .045       0   300.2    .016       0
  301.35     .12       0
Bank Sta=286.8,300.2
XS Rating Curve= 0 ,0
Exp/Cntr=0.3,0.1

Type RM Length L Ch R = 1 ,8614.6  ,343.2,339,336.1
XS GIS Cut Line= 3
     2053454.252       233590.28     2053536.717      233952.693
     2053608.331      234011.287
#Sta/Elev= 30
       0 1614.09    45.6 1591.68    68.5 1582.86    81.5 1578.86   127.2 1567.45
   140.2 1565.01   156.5 1560.29   166.3 1556.54   176.1  1553.7   182.6 1552.95
   195.6 1553.67   202.1 1555.01   208.7 1555.57  235.991555.766   270.6  1555.1
  277.131555.352  288.661556.151   296.7 1558.44   306.5 1563.28   316.2 1564.23
   319.5 1565.65     326 1571.06  343.561577.147   355.4 1581.49   368.4 1587.03
   390.8 1594.56     410 1600.14   441.9 1608.53     461 1614.34   464.2  1614.8
#Mann= 7 ,-1 , 0
       0     .12       0   176.1    .045       0   195.6     .12       0
  235.99     .06       0  277.13     .12       0  288.66    .016       0
  343.56     .12       0
Bank Sta=176.1,195.6
XS Rating Curve= 0 ,0
Exp/Cntr=0.3,0.1

Type RM Length L Ch R = 1 ,8275.6  ,270.5,263.6,256.3
XS GIS Cut Line= 3
     2053145.007      233673.831     2053255.684      234008.032
     2053247.003      234153.431
#Sta/Elev= 30
       0 1627.59    35.9 1603.94    58.7 1590.34   107.6 1567.36   120.6 1560.05
   136.9 1552.93   143.4 1551.24   153.2 1549.97   172.8 1550.66   182.2 1548.53
   192.3 1547.69   198.8 1548.42   215.1 1550.55     251 1551.58   286.9 1553.64
   309.7 1553.86  319.681555.139  332.931557.265   342.3 1558.42   355.3 1558.89
     365 1560.14   375.91560.407   381.2 1560.78   387.7 1562.49   390.9 1564.63
   397.4 1571.61   400.6  1573.6   403.8 1574.75   449.2 1587.93   497.7 1599.98
#Mann= 6 ,-1 , 0
       0     .12       0   182.2    .045       0   198.8     .12       0
  319.68     .06       0  332.93    .016       0   375.9     .12       0
Bank Sta=182.2,198.8
XS Rating Curve= 0 ,0
Exp/Cntr=0.3,0.1

Type RM Length L Ch R = 1 ,8012    ,179.2,183.7,185.1
XS GIS Cut Line= 2
     2052885.675      233818.145     2053143.922      234219.621
#Sta/Elev= 30
       0 1592.12    19.6  1588.2    45.8 1581.72    71.9 1576.54    94.8  1568.3
   104.6 1565.59     121 1558.52     134 1553.98   143.9 1551.61   153.7  1550.3
   156.9 1548.72   160.2 1545.67   163.5 1544.72   173.3 1544.47   181.8 1544.92
   192.9  1546.9  208.211546.258  282.931547.233   300.8 1547.73  309.561548.766
   317.2 1551.07  337.531560.514     340 1561.44   349.8 1562.16   353.1 1563.68
   359.7 1569.19  368.481572.827   402.2  1582.9   431.6 1592.98   477.4 1605.56
#Mann= 8 ,-1 , 0
       0     .12       0   163.5    .045       0   181.8     .12       0
  208.21     .07       0  282.93     .06       0  309.56     .12       0
  337.53    .016       0  368.48     .12       0
Bank Sta=163.5,181.8
XS Rating Curve= 0 ,0
Exp/Cntr=0.3,0.1

Type RM Length L Ch R = 1 ,7828.3  ,182.8,182.8,182.6
XS GIS Cut Line= 2
     2052765.436      233903.529     2052964.682      234318.698
#Sta/Elev= 30
       0 1579.97    29.4 1571.58    52.3 1564.32      62 1560.69    68.6 1559.42
    71.8 1558.34    81.6 1554.12    84.9 1552.16    88.2 1549.82    94.7 1543.75
      98 1542.64   101.2 1542.34   107.8 1542.42   114.5 1543.11   124.1 1544.18
  130.061544.152  290.311545.953  292.351545.996   300.5 1546.17     307 1546.88
   313.5 1548.87  325.121553.984   333.1 1557.06   342.9 1557.74   346.2 1558.75
   349.5 1561.16  353.981563.345   382.1 1572.42   411.5 1580.57   460.5 1591.96
#Mann= 8 ,-1 , 0
       0     .12       0    94.7    .045       0   114.5     .12       0
  130.06     .07       0  290.31     .06       0  292.35     .12       0
  325.12    .016       0  353.98     .12       0
#XS Ineff= 2 , 0
                          218.04         1551.69
Permanent Ineff=
       F       F
Bank Sta=94.7,114.5
XS Rating Curve= 0 ,0
Exp/Cntr=0.3,0.1

Type RM Length L Ch R = 1 ,7645.5  ,166.2,165.6,163.6
XS GIS Cut Line= 2
      2052590.74      233949.102     2052789.985      234364.271
#Sta/Elev= 30
       0 1579.61     9.8 1578.58   17.811574.561    29.4 1570.68    52.3 1561.55
    68.6 1553.41    81.6 1544.04    84.9  1542.7   100.6 1541.07     111  1540.3
   115.6 1540.99   120.8 1543.22   124.1 1543.77   143.7  1542.9   159.31543.279
   241.7 1544.21   267.8 1545.27   277.6 1546.37   290.7 1549.35   297.2 1552.13
     307 1558.51  309.671559.481   323.3  1560.9   326.6 1562.19   333.1 1568.08
   336.4 1570.27  343.281573.329     418 1605.89   434.4 1612.49   460.5 1619.13
#Mann= 7 ,-1 , 0
       0    .016       0   17.81     .12       0   100.6    .045       0
   115.6     .12       0   159.3     .07       0  309.67    .016       0
  343.28     .12       0
Bank Sta=100.6,115.6
XS Rating Curve= 0 ,0
Exp/Cntr=0.3,0.1

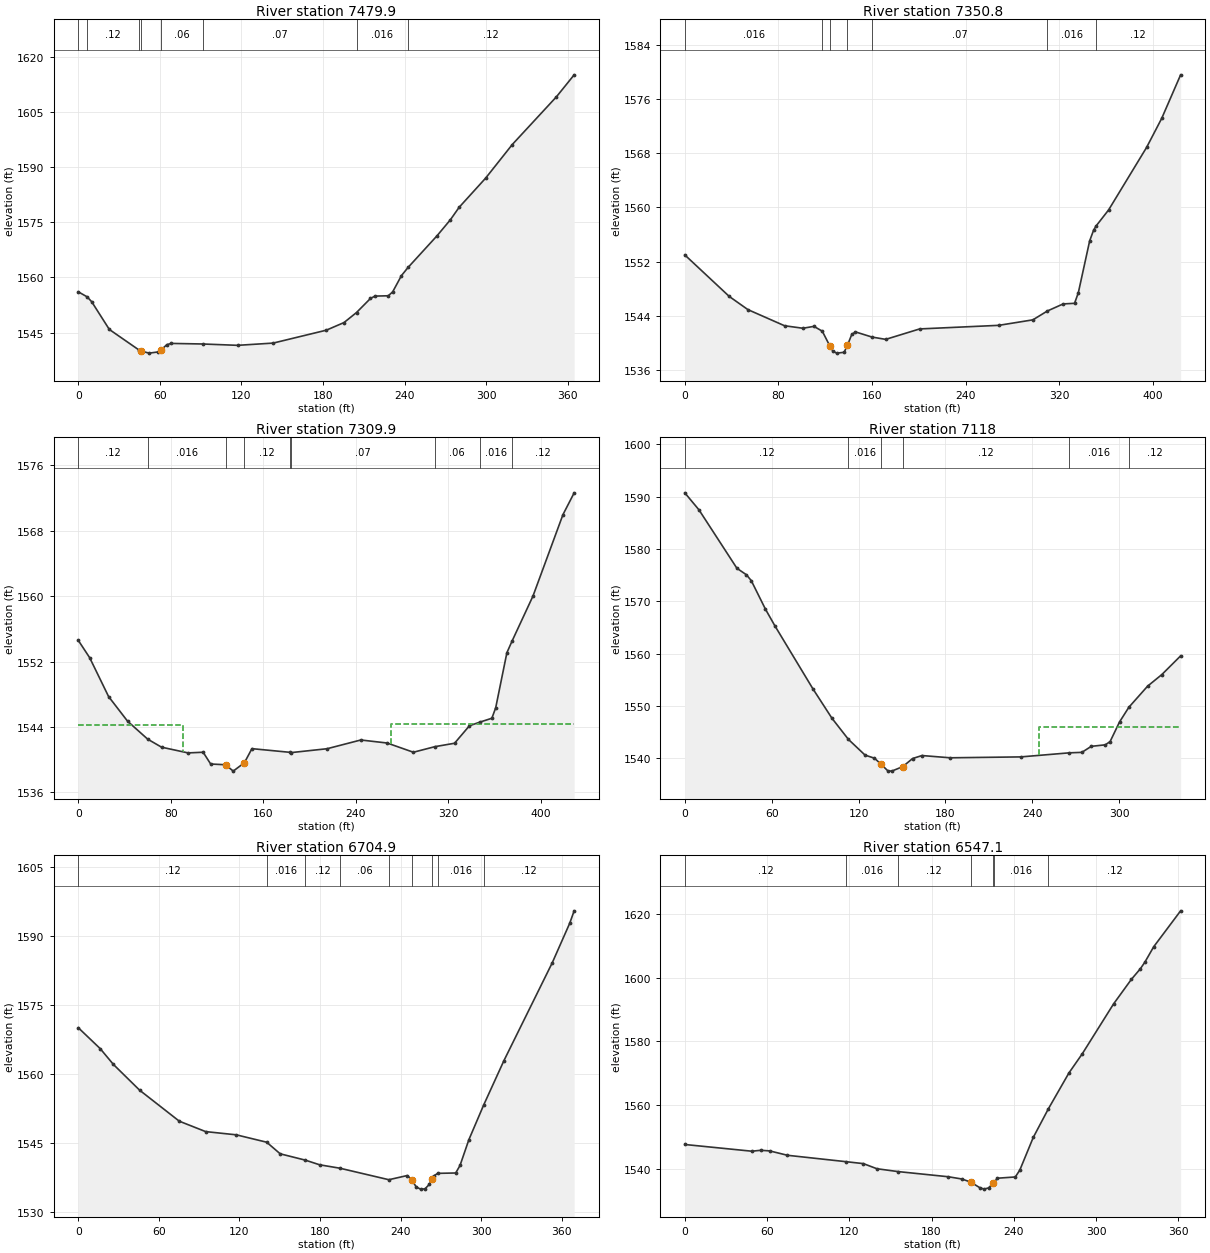
Type RM Length L Ch R = 1 ,7479.9  ,98.5,129.1,139.6
XS GIS Cut Line= 2
     2052484.764      234094.158     2052667.892      234409.592
#Sta/Elev= 30
       0 1556.07     6.5  1554.7     9.8 1553.39    22.8 1545.84   44.381540.311
    46.1 1539.96    52.1  1539.4    58.6 1539.72    61.1 1540.36    65.1  1541.7
    68.4 1542.04   91.381541.887   117.2 1541.52   143.3 1542.13   182.4 1545.64
   195.4 1547.71  204.621550.443   214.9 1554.28   218.2 1554.91     228    1555
   231.2 1556.06   237.7  1560.5  242.521562.697   263.8  1571.3   273.6 1575.64
   280.1 1579.06   299.6    1587   319.2 1596.14   351.7 1609.13   364.7 1615.09
#Mann= 8 ,-1 , 0
       0    .016       0     6.5     .12       0   44.38     .06       0
    46.1    .045       0    61.1     .06       0   91.38     .07       0
  204.62    .016       0  242.52     .12       0
Bank Sta=46.1,61.1
XS Rating Curve= 0 ,0
Exp/Cntr=0.3,0.1

Type RM Length L Ch R = 1 ,7350.8  ,62.4,40.9,38.9
XS GIS Cut Line= 5
     2052466.318      234108.264     2052438.627      234154.516
     2052416.925        234206.6     2052439.712      234379.126
     2052543.878      234471.357
#Sta/Elev= 30
       0    1553      38 1546.87    53.9 1544.93    85.2 1542.55   100.9 1542.18
   110.3 1542.46  117.441541.746   123.9 1539.56   126.4 1538.82   129.7 1538.51
   136.1 1538.63   138.9 1539.66   142.6 1541.26   145.8 1541.64  159.861540.882
   171.6 1540.54   200.6 1542.08   268.2 1542.61   297.3 1543.42  309.751544.732
   323.2 1545.77   332.9 1545.86   336.1  1547.4   345.8 1555.07   349.1 1556.62
   351.2 1557.25     362 1559.64   394.4 1568.85   407.3 1573.13   423.5 1579.57
#Mann= 7 ,-1 , 0
       0    .016       0  117.44     .12       0   123.9    .045       0
   138.9     .12       0  159.86     .07       0  309.75    .016       0
   351.2     .12       0
Bank Sta=123.9,138.9
XS Rating Curve= 0 ,0
Exp/Cntr=0.3,0.1

Type RM Length L Ch R = 1 ,7309.9  ,207.2,192,171.9
XS GIS Cut Line= 4
     2052418.574      234112.604     2052376.257      234204.835
     2052404.989      234391.062     2052509.156      234483.292
#Sta/Elev= 30
       0 1554.59     9.8 1552.48    26.2 1547.72    42.6 1544.71   60.03 1542.51
      72 1541.53    94.9 1540.83     108 1540.91   114.5 1539.47   127.5 1539.38
     134  1538.6   143.7 1539.63   150.2 1541.35  182.971540.903  184.32 1540.87
   215.2 1541.34   244.4 1542.41   267.2 1542.04   289.9 1540.91   308.51541.593
   325.5 1542.01   338.4 1544.15   347.3 1544.59   357.8 1545.07   361.1 1546.34
   370.8 1553.09  375.271554.509   393.4 1560.03   419.3 1569.98     429 1572.65
#Mann= 9 ,-1 , 0
       0     .12       0   60.03    .016       0   127.5    .045       0
   143.7     .12       0  182.97     .06       0  184.32     .07       0
   308.5     .06       0   347.3    .016       0  375.27     .12       0
#XS Ineff= 2 , 0
            90.2 1544.27   270.6         1544.38
Permanent Ineff=
       F       F
Bank Sta=127.5,143.7
XS Rating Curve= 0 ,0
Exp/Cntr=0.3,0.1

Type RM Length L Ch R = 1 ,7118    ,406.5,413,420.8
XS GIS Cut Line= 4
     2052187.976      234305.341      2052292.62      234394.664
     2052304.801      234399.755     2052453.818      234520.185
#Sta/Elev= 30
       0 1590.75     9.8 1587.49      36 1576.32    42.6 1575.07    45.9 1573.96
    55.7  1568.5    62.2 1565.32    88.4  1553.3   101.6 1547.65  113.041543.586
   124.5 1540.59     131    1540   135.5 1538.86   140.2 1537.59   142.9 1537.53
   150.5 1538.39   157.3 1539.94   163.8 1540.51   183.3 1540.08     232 1540.25
  265.541541.029   274.2 1541.12   280.7 1542.27   290.4 1542.56   293.7 1543.18
   300.2 1546.93  306.651549.742   319.6 1553.78   329.4 1555.99   342.4 1559.57
#Mann= 6 ,-1 , 0
       0     .12       0  113.04    .016       0   135.5    .045       0
   150.5     .12       0  265.54    .016       0  306.65     .12       0
#XS Ineff= 2 , 0
                           244.6         1545.96
Permanent Ineff=
       F       F
Bank Sta=135.5,150.5
XS Rating Curve= 0 ,0
Exp/Cntr=0.3,0.1

Type RM Length L Ch R = 1 ,6704.9  ,163.1,157.8,152.3
XS GIS Cut Line= 2
     2051994.746      234481.527     2052210.328      234781.253
#Sta/Elev= 30
       0 1570.08    16.3 1565.54    26.1 1562.11    45.7 1556.49    75.2 1549.76
    94.8  1547.5   117.6  1546.8  140.271545.192   150.3 1542.67  169.111541.287
   179.7 1540.28  194.811539.536   231.21537.038     245 1537.95   248.3 1537.01
   251.6 1535.46   254.8 1534.99   258.1 1535.04   261.4 1536.04  263.64 1537.22
   264.6 1537.84  267.59 1538.42     281  1538.5   284.2 1540.13   290.8 1545.74
  301.971553.376   316.9 1562.93   352.9 1584.22   365.9 1592.81   369.2 1595.51
#Mann= 9 ,-1 , 0
       0     .12       0  140.27    .016       0  169.11     .12       0
  194.81     .06       0   231.2     .12       0   248.3    .045       0
  263.64     .12       0  267.59    .016       0  301.97     .12       0
Bank Sta=248.3,263.64
XS Rating Curve= 0 ,0
Exp/Cntr=0.3,0.1

Type RM Length L Ch R = 1 ,6547.1  ,165.6,163.3,159.1
XS GIS Cut Line= 2
      2051867.88      234657.989     2052142.403      234893.449
#Sta/Elev= 30
       0 1547.57    48.9 1545.46    55.4 1545.75    61.9 1545.56    74.9 1544.18
  117.681542.168   130.3 1541.56   140.1 1539.96  155.311539.073   192.2 1537.44
     202 1536.74   208.5 1535.78     215 1534.05   218.3 1533.55   221.6 1533.94
   224.8 1535.34  225.451535.662   228.1 1536.98   241.1 1537.37   244.4 1539.54
   254.2 1549.79  265.251558.795   280.2 1570.03     290 1576.09   312.8 1591.74
   325.8 1599.46   332.3 1602.76   335.6 1604.83   342.1 1609.71   361.7 1620.97
#Mann= 7 ,-1 , 0
       0     .12       0  117.68    .016       0  155.31     .12       0
   208.5    .045       0   224.8     .12       0  225.45    .016       0
  265.25     .12       0
Bank Sta=208.5,224.8
XS Rating Curve= 0 ,0
Exp/Cntr=0.3,0.1

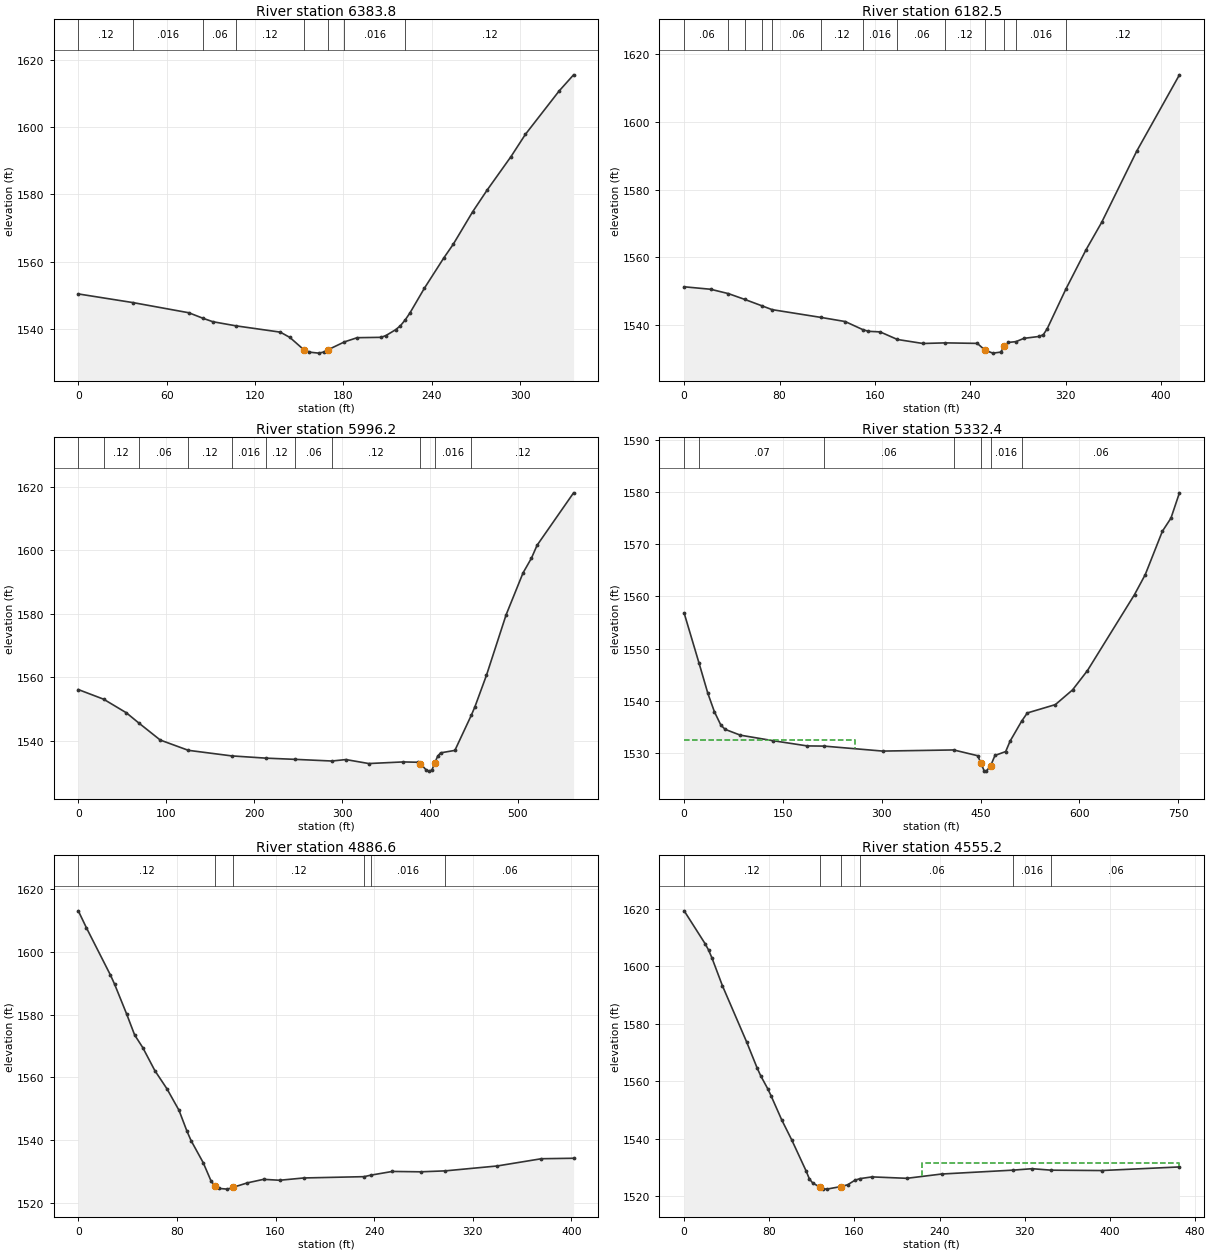
Type RM Length L Ch R = 1 ,6383.8  ,196.1,201.3,205.5
XS GIS Cut Line= 2
     2051796.151       234830.86     2052080.668      235010.291
#Sta/Elev= 30
       0 1550.43   37.231547.852    75.1 1544.84   84.58 1543.22    91.4 1542.18
  107.071540.961   137.2 1539.09   143.7 1537.52   153.5 1533.74   156.8 1533.16
   163.3 1532.86   166.6 1533.17   169.8  1533.9   180.81536.203   189.4 1537.44
   205.7 1537.55     209 1538.09   215.5  1539.8   218.8 1540.99   222.1 1542.76
   225.3 1544.82   235.1 1552.15   248.2 1561.08   254.7  1565.2   267.8 1574.78
   277.6  1581.2   293.9  1591.2   303.7 1597.81   326.6 1610.68   336.4 1615.46
#Mann= 8 ,-1 , 0
       0     .12       0   37.23    .016       0   84.58     .06       0
  107.07     .12       0   153.5    .045       0   169.8     .12       0
   180.8    .016       0   222.1     .12       0
Bank Sta=153.5,169.8
XS Rating Curve= 0 ,0
Exp/Cntr=0.3,0.1

Type RM Length L Ch R = 1 ,6182.5  ,173.2,186.3,196.8
XS GIS Cut Line= 3
     2051687.541      234869.577     2051677.125      234938.588
     2051925.389      235178.822
#Sta/Elev= 30
       0 1551.25    22.2 1550.52   37.151549.228   50.881547.508   65.361545.607
   73.721544.496  114.821542.192     135 1540.98  149.661538.608   154.5 1538.09
   164.3 1537.92  178.791535.677   200.2 1534.49  218.941534.671   245.8 1534.52
   252.3 1532.51   258.8 1531.64   265.3 1531.93   268.6 1533.62   271.9  1534.8
   278.31535.047   284.9 1536.01   297.9 1536.58   301.2 1537.12   304.4 1538.84
     3201550.524     337 1562.21   350.1  1570.3   379.4  1591.3   415.3 1613.91
#Mann= 13 ,-1 , 0
       0     .06       0   37.15     .12       0   50.88     .06       0
   65.36     .12       0   73.72     .06       0  114.82     .12       0
  149.66    .016       0  178.79     .06       0  218.94     .12       0
   252.3    .045       0   268.6     .12       0   278.3    .016       0
     320     .12       0
Bank Sta=252.3,268.6
XS Rating Curve= 0 ,0
Exp/Cntr=0.3,0.1

Type RM Length L Ch R = 1 ,5996.2  ,637.6,663.8,676.7
XS GIS Cut Line= 4
     2051627.125      234847.413     2051607.594      234997.152
     2051746.482      235281.441     2051835.892      235316.163
#Sta/Elev= 30
       0 1556.13    28.81553.094    54.6 1548.82   69.08 1545.54    93.2 1540.23
  125.111536.994  174.531535.235  213.381534.529  246.261534.152  288.471533.623
   304.3 1534.08   330.4 1532.83   369.6 1533.34   385.9 1533.24   389.1 1532.82
   395.6 1530.82   398.9 1530.44   402.2 1530.78   405.4 1533.04   408.7 1535.12
     412 1536.19   428.3 1536.97  447.091548.107   451.1 1550.72   464.2 1560.61
   486.6  1579.7   505.8 1592.86   515.4 1597.53   521.8 1601.58   563.3 1618.09
#Mann= 11 ,-1 , 0
       0     .06       0    28.8     .12       0   69.08     .06       0
  125.11     .12       0  174.53    .016       0  213.38     .12       0
  246.26     .06       0  288.47     .12       0   389.1    .045       0
   405.4    .016       0  447.09     .12       0
Bank Sta=389.1,405.4
XS Rating Curve= 0 ,0
Exp/Cntr=0.3,0.1

Type RM Length L Ch R = 1 ,5332.4  ,460.6,445.9,420.9
XS GIS Cut Line= 3
     2051506.465      234820.069     2051217.706      235303.822
     2051290.319      235477.621
#Sta/Elev= 30
       0  1556.8   22.481547.263      36 1541.42    45.9 1537.91    55.7 1535.35
    62.2 1534.54    85.2 1533.43   134.3 1532.38   186.7 1531.37  212.261531.332
   301.3 1530.38  409.091530.597   445.5 1529.49   450.3 1528.11   455.3  1526.6
   458.6 1526.54   465.3 1527.61   471.7 1529.54     488 1530.29   494.6 1532.27
  512.291536.127   520.8 1537.68   563.4 1539.28   589.4 1542.09   612.1  1545.8
   683.5 1560.35   699.8 1564.17   725.8 1572.48   738.8 1574.99   751.7 1579.84
#Mann= 7 ,-1 , 0
       0     .12       0   22.48     .07       0  212.26     .06       0
  409.09    .016       0   450.3    .045       0   465.3    .016       0
  512.29     .06       0
#XS Ineff= 2 , 0
          259.09 1532.46
Permanent Ineff=
       F       F
Bank Sta=450.3,465.3
XS Rating Curve= 0 ,0
Exp/Cntr=0.3,0.1

Type RM Length L Ch R = 1 ,4886.6  ,330.8,331.4,331.2
XS GIS Cut Line= 2
      2050959.46      234880.645     2051024.781      235277.129
#Sta/Elev= 30
       0 1613.09     6.5 1607.75    26.1  1592.6    29.4 1589.74    39.2 1580.22
    45.7 1573.52    52.3 1569.49    62.1 1562.16    71.9 1556.37    81.7  1549.5
    88.2  1542.8    91.5 1539.84   101.3 1532.83   107.8 1526.89   110.8 1525.44
   114.3  1524.6   120.9 1524.38   125.8 1524.98   137.2 1526.38   150.3  1527.5
   163.4 1527.21     183 1527.94  231.851528.354  237.381528.838   254.8 1530.02
   277.7  1529.9  297.751530.202   339.8 1531.76   375.7 1534.07   401.8 1534.22
#Mann= 6 ,-1 , 0
       0     .12       0   110.8    .045       0   125.8     .12       0
  231.85     .06       0  237.38    .016       0  297.75     .06       0
Bank Sta=110.8,125.8
XS Rating Curve= 0 ,0
Exp/Cntr=0.3,0.1

Type RM Length L Ch R = 1 ,4555.2  ,258.4,247.5,236.6
XS GIS Cut Line= 3
     2050638.279      234906.687     2050701.864      235313.588
     2050740.927      235350.046
#Sta/Elev= 30
       0 1619.24    19.6 1607.86    22.9 1605.64    26.2 1602.78      36 1593.15
    58.8 1573.58    68.6 1564.58    71.9 1561.92    78.4 1557.49    81.7 1554.91
    91.5 1546.71   101.3 1539.44   114.4 1528.97   117.7 1526.03   120.9  1524.6
   127.5 1523.25   130.7 1522.66     134 1522.52   147.1  1523.4   153.6 1524.03
   160.2 1525.56  165.021526.163   176.5 1526.77   209.2 1526.28   241.9 1527.77
  308.97 1529.12   326.9 1529.62  344.881529.105   392.2 1528.98   465.3 1530.23
#Mann= 6 ,-1 , 0
       0     .12       0   127.5    .045       0   147.1     .12       0
  165.02     .06       0  308.97    .016       0  344.88     .06       0
#XS Ineff= 2 , 0
                          223.01         1531.46
Permanent Ineff=
       F       F
Bank Sta=127.5,147.1
XS Rating Curve= 0 ,0
Exp/Cntr=0.3,0.1

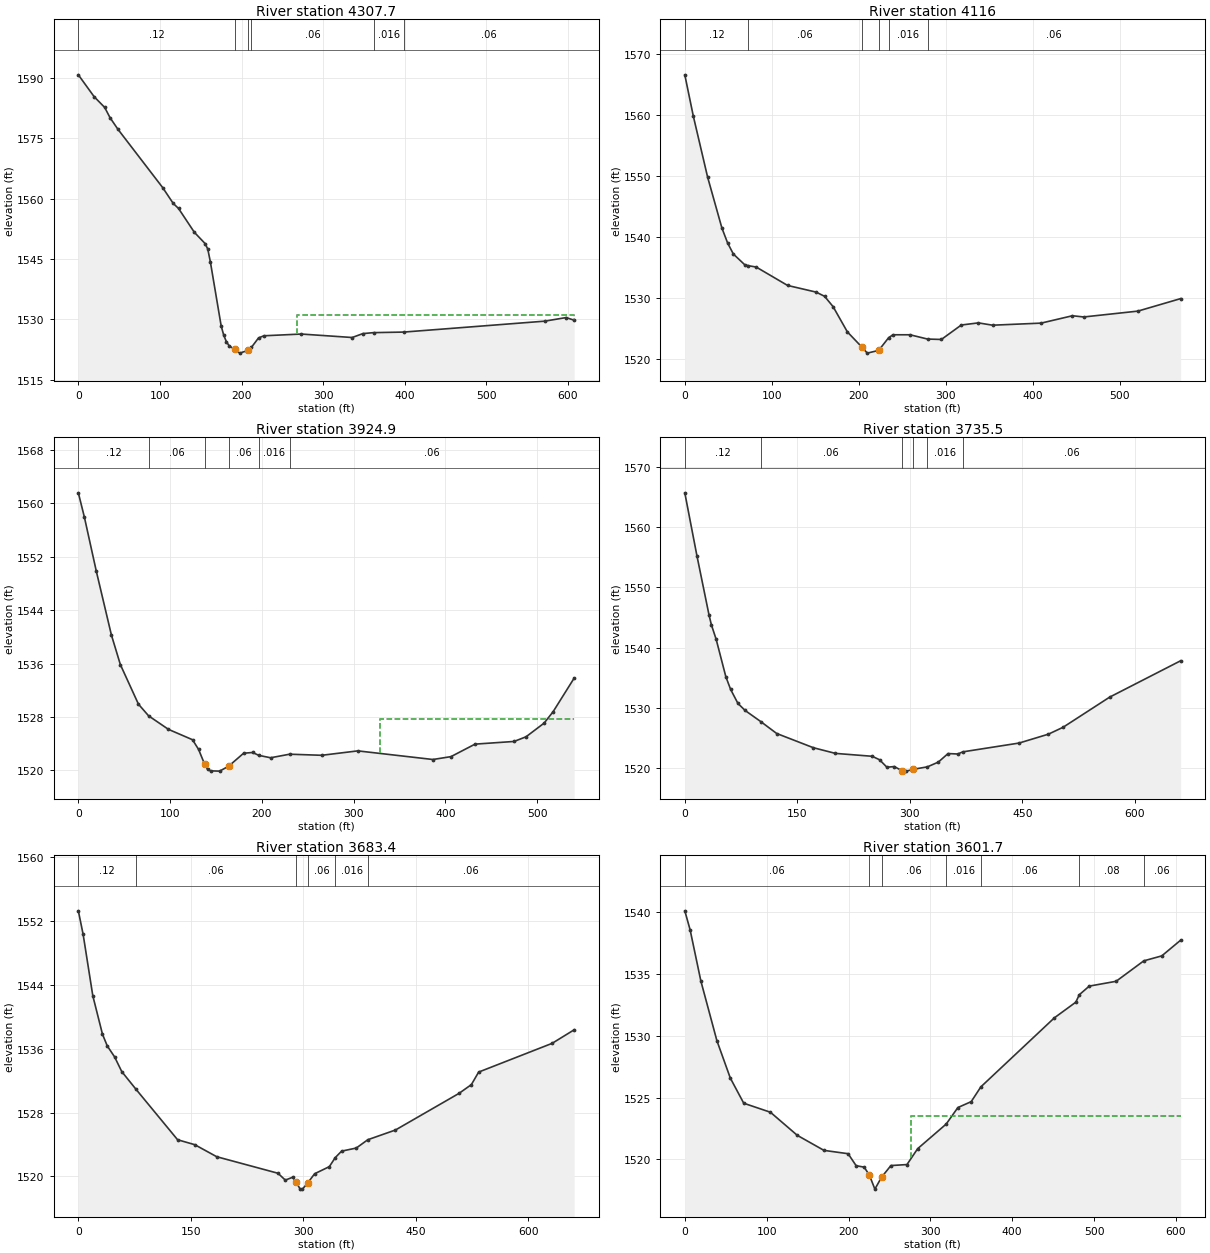
Type RM Length L Ch R = 1 ,4307.7  ,196.7,191.7,186.6
XS GIS Cut Line= 3
     2050436.456      234943.579     2050397.394      235080.298
     2050675.172      235453.562
#Sta/Elev= 30
       0 1590.74    19.4  1585.3    32.3 1582.64    38.8 1580.11    48.5 1577.22
   103.4 1562.71   116.3 1558.79   122.8 1557.54   142.2 1551.61   155.3 1548.83
   158.6 1547.46   161.8 1544.25     175 1528.38   178.2 1526.03   181.5  1524.4
   184.8 1523.43   191.4 1522.54   197.9 1521.61   207.7  1522.3  212.121523.055
   220.8 1525.39   227.4 1525.92   273.2 1526.35   335.5 1525.49   348.6 1526.46
  361.68  1526.7  398.84 1526.84   571.4 1529.55   597.6 1530.44   607.5 1529.79
#Mann= 6 ,-1 , 0
       0     .12       0   191.4    .045       0   207.7     .12       0
  212.12     .06       0  361.68    .016       0  398.84     .06       0
#XS Ineff= 2 , 0
                          268.47         1531.11
Permanent Ineff=
       F       F
Bank Sta=191.4,207.7
XS Rating Curve= 0 ,0
Exp/Cntr=0.3,0.1

Type RM Length L Ch R = 1 ,4116    ,177.6,191.1,204.3
XS GIS Cut Line= 3
     2050231.812      235113.067     2050260.371      235227.621
     2050604.121       235520.59
#Sta/Elev= 30
       0 1566.53     9.8 1559.75    26.2 1549.76    42.6 1541.42    49.2 1538.95
    55.8 1537.14    68.9 1535.38   73.021535.225      82 1535.01   118.1 1531.99
   150.8  1530.9   160.6 1530.21   170.4 1528.51   186.8 1524.37   203.2 1521.92
   209.7 1520.89   222.8 1521.34  234.25 1523.43   239.2  1523.9   258.8  1523.9
  278.941523.197   294.8 1523.13   317.7  1525.5   337.3 1525.85   353.7 1525.47
   409.4 1525.81   445.4 1527.02   458.4 1526.82   520.6 1527.78   569.7 1529.83
#Mann= 6 ,-1 , 0
       0     .12       0   73.02     .06       0   203.2    .045       0
   222.8     .06       0  234.25    .016       0  278.94     .06       0
Bank Sta=203.2,222.8
XS Rating Curve= 0 ,0
Exp/Cntr=0.3,0.1

Type RM Length L Ch R = 1 ,3924.9  ,188.8,189.4,189
XS GIS Cut Line= 2
     2050100.215      235139.079     2050269.486        235652.1
#Sta/Elev= 30
       0 1561.55     6.6 1557.91    19.6 1549.81      36 1540.29    45.8 1535.84
    65.5 1529.92   76.581528.171    98.2 1526.15   124.4  1524.6     131 1523.15
   137.5 1520.97   140.8 1520.16   144.1 1519.94   153.9  1519.9   163.7 1520.63
   180.1 1522.58   189.9 1522.69  196.651522.257   209.5  1521.9  230.211522.433
   265.2 1522.27   304.5 1522.93   386.3 1521.64     406 1522.07   432.2 1523.94
   474.7 1524.34   487.8 1525.04   507.5 1527.09   517.3  1528.8   540.2 1533.82
#Mann= 6 ,-1 , 0
       0     .12       0   76.58     .06       0   137.5    .045       0
   163.7     .06       0  196.65    .016       0  230.21     .06       0
#XS Ineff= 2 , 0
                          328.98         1527.66
Permanent Ineff=
       F       F
Bank Sta=137.5,163.7
XS Rating Curve= 0 ,0
Exp/Cntr=0.3,0.1

Type RM Length L Ch R = 1 ,3735.5  ,52.6,52.1,51.9
XS GIS Cut Line= 3
     2049957.073      235113.067     2049940.146      235214.629
     2050118.531      235743.275
#Sta/Elev= 30
       0 1565.75    16.1 1555.32    32.2 1545.48    35.4 1543.81    41.8 1541.38
    54.7 1535.16    61.1 1533.04    70.8 1530.72    80.4 1529.54  101.221527.697
   122.5 1525.71   171.5 1523.34   200.8  1522.4   249.8 1521.92   259.6 1521.34
   269.4  1520.1   279.2 1520.21   289.1 1519.55   295.5 1519.45   304.1 1519.75
  323.311520.158   337.9 1520.95   350.9 1522.37     364  1522.3  370.391522.653
   445.6 1524.12   484.7  1525.6   504.3 1526.75   566.3 1531.76   660.9 1537.81
#Mann= 6 ,-1 , 0
       0     .12       0  101.22     .06       0   289.1    .045       0
   304.1     .06       0  323.31    .016       0  370.39     .06       0
Bank Sta=289.1,304.1
XS Rating Curve= 0 ,0
Exp/Cntr=0.3,0.1

Type RM Length L Ch R = 1 ,3683.4  ,83.9,81.8,79.8
XS GIS Cut Line= 3
     2049910.198      235132.598     2049893.271       235234.16
     2050071.656      235762.806
#Sta/Elev= 30
       0 1553.29     6.4 1550.34    19.3 1542.64    32.2 1537.82    38.6 1536.35
    48.3 1534.99    57.9 1533.14   76.991530.909   132.3  1524.6   155.2 1523.98
   184.5 1522.47   266.1  1520.4   275.9 1519.54   285.7  1519.9   290.6  1519.3
   295.5 1518.42   298.7 1518.41   305.6 1519.17     315 1520.34   334.6 1521.23
  342.421522.356   350.9 1523.17   370.5 1523.56  385.841524.601   422.7 1525.82
   507.6 1530.42   523.9 1531.51   533.6 1533.08   631.5 1536.68   660.9 1538.38
#Mann= 6 ,-1 , 0
       0     .12       0   76.99     .06       0   290.6    .045       0
   305.6     .06       0  342.42    .016       0  385.84     .06       0
Bank Sta=290.6,305.6
XS Rating Curve= 0 ,0
Exp/Cntr=0.3,0.1

Type RM Length L Ch R = 1 ,3601.7  ,113.9,112.1,109.8
XS GIS Cut Line= 3
      2049781.07      235213.364      2049940.62      235575.472
     2050040.406      235760.202
#Sta/Elev= 30
       0 1540.13     6.5 1538.59    19.6 1534.45    39.2 1529.61    55.6 1526.58
      72 1524.54   104.6 1523.81   137.4 1521.94     170 1520.72   199.5 1520.45
   209.3 1519.48   219.1 1519.36   225.4 1518.73   232.2 1517.58   240.4 1518.55
   251.8 1519.49   271.4 1519.57   284.5 1520.86  319.28 1522.85   333.6 1524.19
   349.9 1524.67  361.651525.865   451.5 1531.46   477.7 1532.73   481.91533.329
   494.1 1534.03   526.9 1534.42  560.711536.077   582.7 1536.48   605.7 1537.75
#Mann= 7 ,-1 , 0
       0     .06       0   225.4    .045       0   240.4     .06       0
  319.28    .016       0  361.65     .06       0   481.9     .08       0
  560.71     .06       0
#XS Ineff= 2 , 0
                          276.42         1523.48
Permanent Ineff=
       F       F
Bank Sta=225.4,240.4
XS Rating Curve= 0 ,0
Exp/Cntr=0.3,0.1

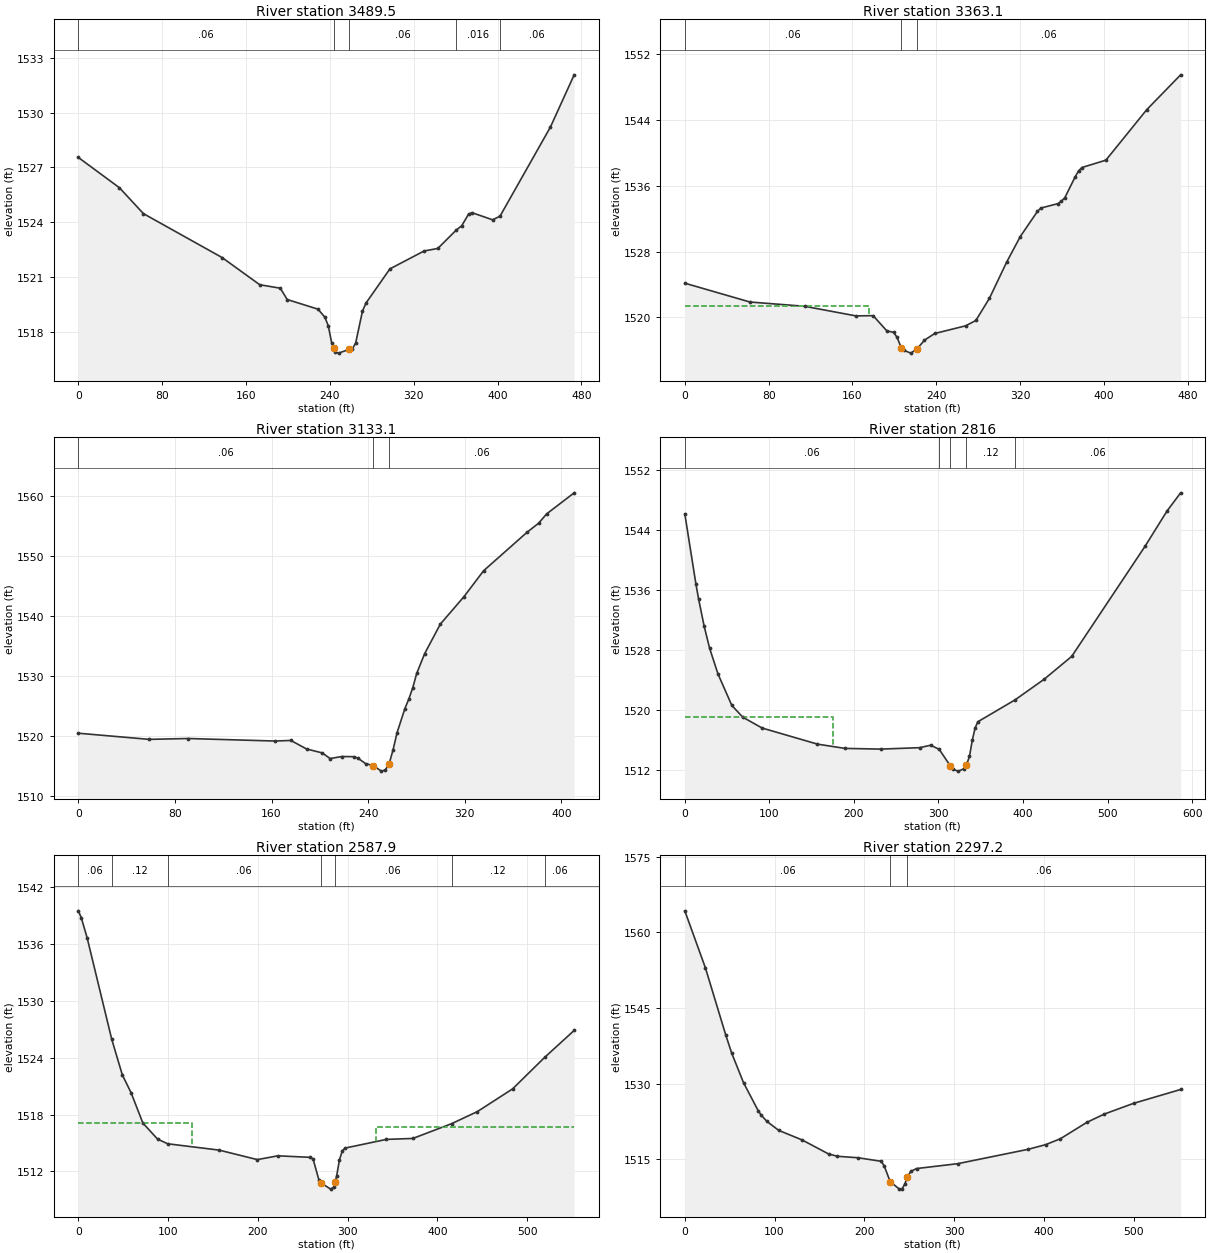
Type RM Length L Ch R = 1 ,3489.5  ,125.6,126.4,124.5
XS GIS Cut Line= 3
     2049654.338      235250.437     2049847.698       235602.65
     2049821.656      235669.056
#Sta/Elev= 30
       0 1527.55    39.2 1525.89    62.1 1524.47   137.2 1522.06   173.1 1520.57
   192.7 1520.38   199.3 1519.76   228.7 1519.23   235.2 1518.79   238.5 1518.32
   241.7 1517.39   243.6  1517.1     245 1516.88   248.3 1516.82   258.6 1517.03
   261.3 1517.04   264.6 1517.37   271.1 1519.12   274.4 1519.56   297.3 1521.44
   329.9 1522.42     343 1522.56  360.391523.556   365.9 1523.81   372.4 1524.45
   375.7 1524.52   395.3 1524.13  402.351524.329   450.4 1529.21   473.1 1532.08
#Mann= 5 ,-1 , 0
       0     .06       0   243.6    .045       0   258.6     .06       0
  360.39    .016       0  402.35     .06       0
Bank Sta=243.6,258.6
XS Rating Curve= 0 ,0
Exp/Cntr=0.3,0.1

Type RM Length L Ch R = 1 ,3363.1  ,221.8,230.1,237.5
XS GIS Cut Line= 3
     2049563.193      235335.072     2049756.552      235687.285
      2049730.51      235753.692
#Sta/Elev= 30
       0 1524.15    62.1 1521.86   114.3 1521.34   163.3 1520.17   179.7  1520.2
   192.7 1518.36   199.3 1518.16   202.5 1517.57   206.5 1516.31   209.1 1515.98
   215.6 1515.64   221.5 1516.14   228.7 1517.22   238.5 1518.03   267.9 1518.96
   277.7 1519.61   290.7 1522.32   307.1 1526.71   320.1 1529.82   336.5 1532.89
   339.7 1533.29   356.1 1533.83   359.3 1534.12   362.6 1534.55   372.4 1537.07
   375.7 1537.81   378.9 1538.22   401.8 1539.12   440.7 1545.25   473.1  1549.5
#Mann= 3 ,-1 , 0
       0     .06       0   206.5    .045       0   221.5     .06       0
#XS Ineff= 2 , 0
          176.14 1521.42
Permanent Ineff=
       F       F
Bank Sta=206.5,221.5
XS Rating Curve= 0 ,0
Exp/Cntr=0.3,0.1

Type RM Length L Ch R = 1 ,3133.1  ,306.6,317,325.8
XS GIS Cut Line= 2
     2049424.434      235379.965     2049492.142      235784.913
#Sta/Elev= 30
       0  1520.5    58.6 1519.48    91.2 1519.62   162.9  1519.2     176  1519.3
     189 1517.88     202 1517.23   208.5 1516.29   218.3 1516.63   228.1  1516.6
   231.4 1516.37   237.9 1515.45   244.4  1515.1   250.9  1514.2   254.2 1514.37
   257.4 1515.45   260.7 1517.78   263.9 1520.56   270.4 1524.58   273.7 1526.19
     277 1528.09   280.2 1530.43   286.8 1533.73   299.8 1538.64   319.3 1543.18
   335.6  1547.5   371.5 1553.88   381.2 1555.41   387.8 1556.95   410.6 1560.45
#Mann= 3 ,-1 , 0
       0     .06       0   244.4    .045       0   257.4     .06       0
Bank Sta=244.4,257.4
XS Rating Curve= 0 ,0
Exp/Cntr=0.3,0.1

Type RM Length L Ch R = 1 ,2816    ,229.5,228.2,226.8
XS GIS Cut Line= 3
     2049238.236       235268.42     2049121.916      235707.656
     2049177.472      235827.448
#Sta/Elev= 30
       0 1546.12    13.1 1536.82    16.3  1534.8    22.9 1531.17    29.4 1528.22
    39.2 1524.84    55.6 1520.64    68.6 1519.07    91.5 1517.63   156.9 1515.49
   189.6 1514.92   232.1 1514.83   277.9 1515.02   290.9 1515.35   300.91514.791
   313.8 1512.64   317.1 1512.13   323.6  1511.9   330.2 1512.23   332.9 1512.66
   336.7 1513.86     340    1516   343.2 1517.58   346.5 1518.46   390.61521.376
     425 1524.12   457.6 1527.16   544.6 1541.85   570.3 1546.49   586.4 1548.91
#Mann= 5 ,-1 , 0
       0     .06       0   300.9     .12       0   313.8    .045       0
   332.9     .12       0   390.6     .06       0
#XS Ineff= 2 , 0
          174.72 1519.12
Permanent Ineff=
       F       F
Bank Sta=313.8,332.9
XS Rating Curve= 0 ,0
Exp/Cntr=0.3,0.1

Type RM Length L Ch R = 1 ,2587.9  ,289.5,290.7,291.4
XS GIS Cut Line= 2
     2048992.471      235241.839     2048883.046       235783.34
#Sta/Elev= 30
       0 1539.46     3.3 1538.73     9.8 1536.62   37.17 1525.94      49 1522.18
    58.8 1520.29    71.9  1517.1    88.3 1515.41   99.591514.917   156.9 1514.25
   199.4 1513.25   222.3 1513.65   258.2 1513.49   261.5 1513.32     268 1511.12
   270.2 1510.81   281.1 1510.14   284.4 1510.33  285.92 1510.86   287.7 1511.48
   290.9 1513.22   294.2  1514.2   297.5 1514.47   343.2 1515.38   372.7 1515.48
  415.781517.034   444.6 1518.31   483.8  1520.7  519.571524.023   552.4 1526.86
#Mann= 7 ,-1 , 0
       0     .06       0   37.17     .12       0   99.59     .06       0
   270.2    .045       0  285.92     .06       0  415.78     .12       0
  519.57     .06       0
#XS Ineff= 2 , 0
          126.14 1517.07  331.53         1516.69
Permanent Ineff=
       F       F
Bank Sta=270.2,285.92
XS Rating Curve= 0 ,0
Exp/Cntr=0.3,0.1

Type RM Length L Ch R = 1 ,2297.2  ,201.8,202.7,202.1
XS GIS Cut Line= 2
     2048710.328      235223.527     2048578.383      235759.985
#Sta/Elev= 30
       0 1564.27    22.9    1553    45.8 1539.56    52.3 1536.04    65.4 1530.22
    81.7 1524.68      85 1523.81    91.5 1522.53   104.6 1520.76   130.8 1518.85
   160.2 1516.08     170 1515.62   192.9 1515.33     219 1514.62   222.3 1513.65
   228.8  1510.6   238.6 1509.18   241.9 1509.11   245.2 1510.15     248 1511.52
   251.7 1512.61   258.2 1513.19     304 1514.15   382.5    1517   402.1 1517.93
   418.4 1519.09   447.8 1522.33   467.4 1523.99   500.1 1526.12   552.4 1528.86
#Mann= 3 ,-1 , 0
       0     .06       0   228.8    .045       0     248     .06       0
Bank Sta=228.8,248
XS Rating Curve= 0 ,0
Exp/Cntr=0.3,0.1