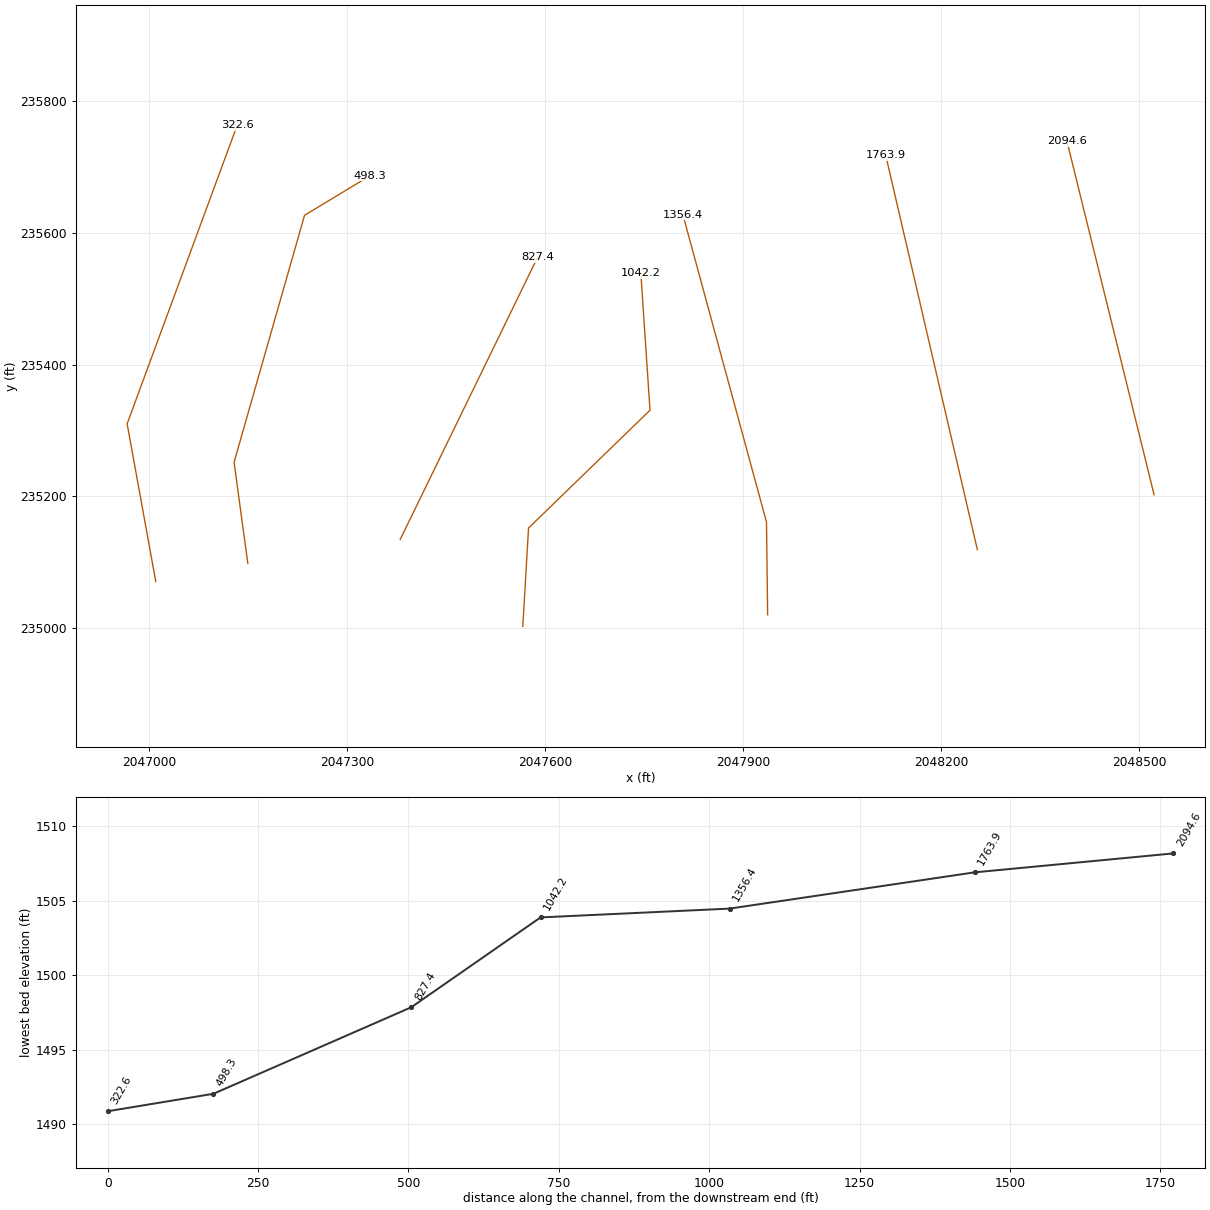
HEC-RAS study WINDCK.prj: WINDCK

--- WINDCK.g01 (geometry) --- (continued)

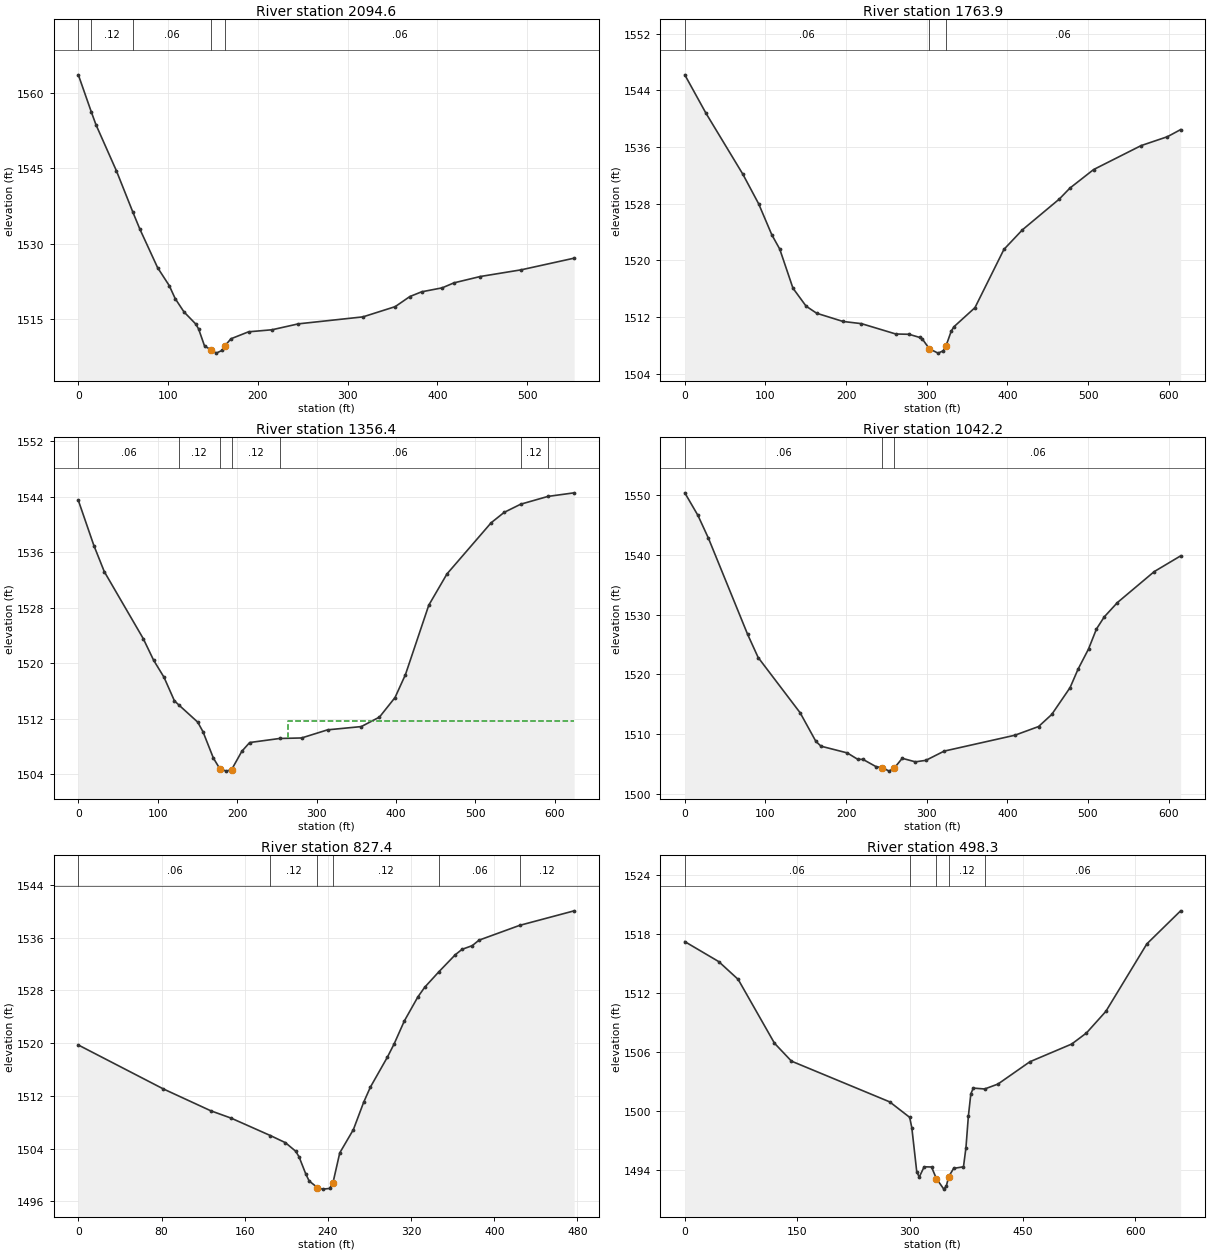
Type RM Length L Ch R = 1 ,2094.6  ,329.9,330.6,329.7
XS GIS Cut Line= 2
     2048522.828      235202.693     2048390.883      235739.152
#Sta/Elev= 30
       0 1563.66   14.35 1556.32    19.6 1553.73    42.5 1544.49   60.911536.208
    68.6 1532.87    88.3 1525.21   101.3 1521.62   107.9 1519.04   117.7 1516.38
   130.8 1513.97     134 1512.98   140.6 1509.59   148.2 1508.78   153.6 1508.16
   160.2  1508.7   163.2 1509.59     170 1511.02   189.6 1512.41   215.8 1512.82
   245.2    1514   317.1 1515.39     353 1517.43   369.4 1519.45   382.5 1520.39
   405.4 1521.18   418.4 1522.17   447.8 1523.44   493.6 1524.78   552.4  1527.1
#Mann= 5 ,-1 , 0
       0     .06       0   14.35     .12       0   60.91     .06       0
   148.2    .045       0   163.2     .06       0
Bank Sta=148.2,163.2
XS Rating Curve= 0 ,0
Exp/Cntr=0.3,0.1

Type RM Length L Ch R = 1 ,1763.9  ,405.8,407.5,408
XS GIS Cut Line= 2
     2048255.033       235119.36     2048116.144      235718.318
#Sta/Elev= 30
       0 1546.17    26.2 1540.76      72 1532.14    91.6 1527.96   107.9 1523.59
   117.7 1521.58   134.1 1516.06   150.4 1513.52   163.5 1512.52   196.2 1511.36
   219.1 1511.05   261.6 1509.59     278 1509.55   291.1 1509.11   294.3 1508.92
   303.3  1507.5     314 1506.89   320.5 1507.22   323.8 1507.88   330.3 1509.97
   333.6  1510.6   359.8 1513.31   395.7 1521.53   418.6 1524.29   464.4 1528.64
   477.5 1530.18   506.9  1532.8   565.8 1536.18   598.5 1537.44   614.8 1538.44
#Mann= 3 ,-1 , 0
       0     .06       0   303.3    .045       0   323.8     .06       0
Bank Sta=303.3,323.8
XS Rating Curve= 0 ,0
Exp/Cntr=0.3,0.1

Type RM Length L Ch R = 1 ,1356.4  ,338,314.2,289.8
XS GIS Cut Line= 3
     2047937.324      235020.402     2047935.588      235161.027
     2047808.852      235628.041
#Sta/Elev= 30
       0 1543.48    19.6 1536.97    32.7 1533.21    81.8 1523.55    94.8 1520.45
   107.9 1517.99     121  1514.6  126.781513.975   150.4 1511.52     157 1510.14
   170.1 1506.34   178.1 1504.83   186.4 1504.46   193.1 1504.69     206 1507.33
   215.8 1508.58  253.491509.165   281.2 1509.24   313.9 1510.41   356.4 1510.88
   379.3 1512.25   398.9 1515.07     412 1518.37   441.4 1528.38   464.3 1532.88
   519.9 1540.25   536.3 1541.75  557.111542.929  591.551544.055   624.5 1544.57
#Mann= 7 ,-1 , 0
       0     .06       0  126.78     .12       0   178.1    .045       0
   193.1     .12       0  253.49     .06       0  557.11     .12       0
  591.55     .06       0
#XS Ineff= 2 , 0
                          264.49         1511.72
Permanent Ineff=
       F       F
Bank Sta=178.1,193.1
XS Rating Curve= 0 ,0
Exp/Cntr=0.3,0.1

Type RM Length L Ch R = 1 ,1042.2  ,207.3,214.8,222.5
XS GIS Cut Line= 4
     2047566.361      235002.795     2047575.041        235152.1
     2047759.069       235330.92      2047745.18      235539.253
#Sta/Elev= 30
       0 1550.31    16.3 1546.54    29.3 1542.74      78 1526.67      91 1522.83
   143.1  1513.6   162.6 1508.83     169 1508.03   201.5 1506.91   214.5 1505.84
     221 1505.83   237.3 1504.61   245.1 1504.45   253.5 1503.87   260.1 1504.43
   269.7 1506.01     286 1505.42     299 1505.67   321.7 1507.21   409.4 1509.86
   438.8 1511.31   455.1 1513.32   477.9 1517.81   487.7 1520.86   500.8 1524.26
   510.6 1527.59   520.3 1529.61   536.6    1532   582.3 1537.17     615 1539.79
#Mann= 3 ,-1 , 0
       0     .06       0   245.1    .045       0   260.1     .06       0
Bank Sta=245.1,260.1
XS Rating Curve= 0 ,0
Exp/Cntr=0.3,0.1

Type RM Length L Ch R = 1 ,827.4   ,323.4,329,332.7
XS GIS Cut Line= 2
     2047380.597      235134.739      2047588.93      235563.559
#Sta/Elev= 30
       0 1519.71    81.6 1513.06   127.4 1509.73   146.9 1508.62  184.741505.971
   199.2 1504.89     209  1503.6   212.2 1502.77   218.8 1500.12     222 1499.08
   229.9 1498.09   235.1 1497.85   241.6 1497.95   244.9 1498.84   251.4 1503.35
   264.5 1506.88   274.3 1510.99   280.8 1513.31   297.2 1517.87   303.7 1519.88
   313.5 1523.36   326.5    1527   333.1 1528.47  346.821530.836   362.5  1533.4
     369 1534.22   378.8 1534.78   385.3 1535.61  424.381537.855   476.8 1540.06
#Mann= 6 ,-1 , 0
       0     .06       0  184.74     .12       0   229.9    .045       0
   244.9     .12       0  346.82     .06       0  424.38     .12       0
Bank Sta=229.9,244.9
XS Rating Curve= 0 ,0
Exp/Cntr=0.3,0.1

Type RM Length L Ch R = 1 ,498.3   ,177.7,175.7,172.7
XS GIS Cut Line= 4
     2047149.694      235098.281     2047128.861      235251.927
     2047235.632      235626.927      2047334.59      235686.823
#Sta/Elev= 30
       0 1517.21    45.2 1515.18    71.1 1513.37   119.5 1506.88   142.1 1505.06
     273 1500.92  299.611499.347   302.5 1498.27     309 1493.84   312.3 1493.27
   318.9 1494.32   328.7  1494.3   335.3 1493.11   345.1 1492.05   348.4 1492.35
   351.6 1493.32   358.2 1494.16   371.3 1494.32   374.6 1496.27   377.8 1499.46
   381.1 1501.74   384.4 1502.32  399.541502.231   417.2 1502.73   459.8    1505
   515.5  1506.8   535.1 1507.92     561 1510.12   615.6 1516.98   660.6 1520.34
#Mann= 5 ,-1 , 0
       0     .06       0  299.61     .12       0   335.3    .045       0
   351.6     .12       0  399.54     .06       0
Bank Sta=335.3,351.6
XS Rating Curve= 0 ,0
Exp/Cntr=0.3,0.1

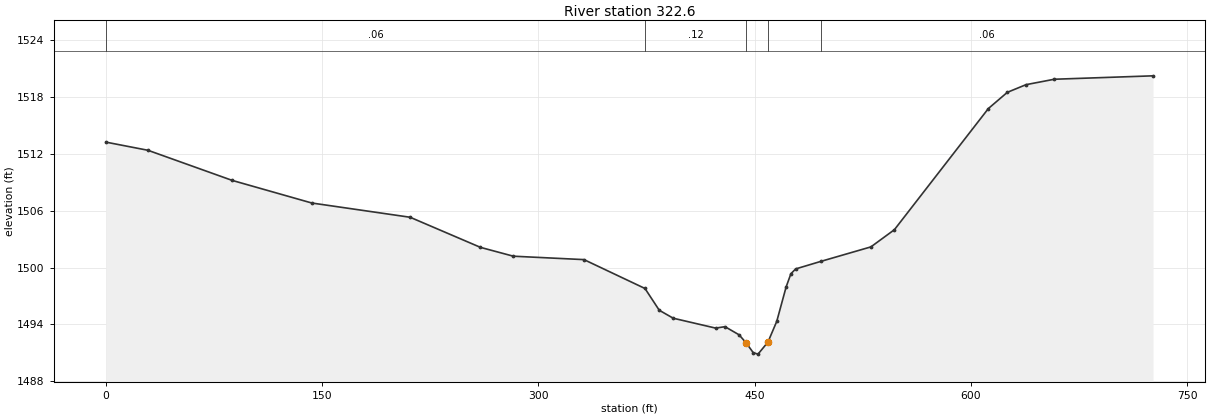
Type RM Length L Ch R = 1 ,322.6   ,321.5,322.6,321.4
XS GIS Cut Line= 3
     2047010.241      235070.749     2046966.838      235310.332
     2047133.505      235763.457
#Sta/Elev= 30
       0  1513.2    29.2 1512.34    87.6 1509.17   142.8 1506.79     211 1505.29
   259.8 1502.12   282.6 1501.19   331.6 1500.83  373.911497.791   383.8  1495.5
   393.5 1494.66   422.9 1493.62   429.4 1493.77   439.2 1492.91   444.2 1492.04
     449 1491.03   452.3 1490.88   459.2 1492.15   465.3 1494.33   471.8 1497.95
   475.1 1499.34   478.4 1499.85  495.681500.635   530.6 1502.17   546.9 1503.98
   612.1 1516.74   625.2 1518.44   638.2 1519.25   657.8 1519.82   726.3 1520.18
#Mann= 5 ,-1 , 0
       0     .06       0  373.91     .12       0   444.2    .045       0
   459.2     .12       0  495.68     .06       0
Bank Sta=444.2,459.2
XS Rating Curve= 0 ,0
Exp/Cntr=0.3,0.1

Chan Stop Cuts=-1
Use User Specified Reach Order=0
Composite Channel Slope=5